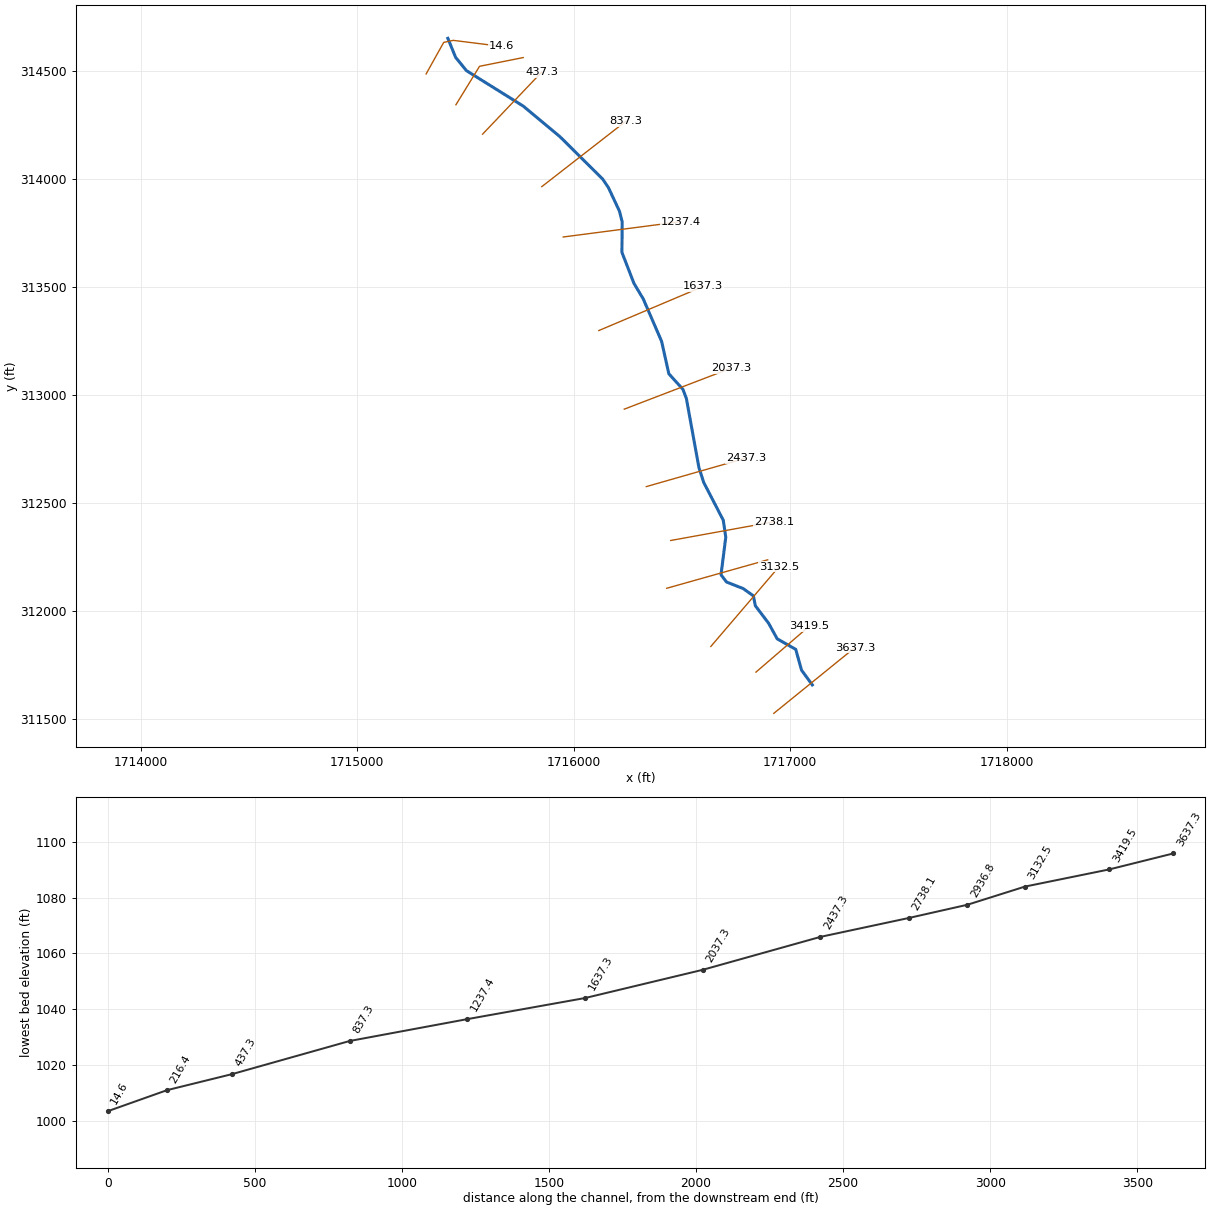
--- GEORGESCRK.prj (project) ---

Proj Title=GEORGESCRK
Current Plan=p01
Default Exp/Contr=0,0
English Units
Geom File=g01
Flow File=f01
Plan File=p01
BEGIN DESCRIPTION:
END DESCRIPTION:
DSS Export Rating Curves= 0
DSS Export Rating Curve Sorted= 0
DSS Export Volume Flow Curves= 0
DXF OffsetX= 0
DXF OffsetY= 0
DXF ScaleX= 0
DXF ScaleY= 0

--- GEORGESCRK.p01 (plan) ---

Plan Title=Floodplain
Program Version=4.00
Geom File=g01
Flow File=f01
K Sum by GR=0
Std Step Tol=0.01
Critical Tol=0.01
Num of Std Step Trials=20
Max Error Tol=0.3
Flow Tol Ratio=0.001
Split Flow NTrial=30
Split Flow Tol=0.02
Split Flow Ratio=0.02
Log Output Level=0
Friction Slope Method=1
Unsteady Friction Slope Method=2
Unsteady Bridges Friction Slope Method=1
Global Log Level=0
CheckData=False
Run HTab=0
Run UNet=0
Run PostProcess=0
UNET Theta=0
UNET Theta Warmup=0
UNET ZTol=0
UNET ZSATol=0
UNET MxIter=0
UNET MaxInSteps=0
UNET DtIC=0
UNET DtMin=0
UNET MaxCRTS=0
UNET WFStab=0
UNET SFStab=0
UNET WFX=0
UNET SFX=0
UNET DSS MLevel=0
UNET DZMax Abort=0
UNET Convert EG Bridges=0
UNET Use Existing IB Tables=0
UNET Froude Limit=0
UNET Froude Power=0
Write IC File=0
Echo Input=False
Echo Output=False
Write Detailed=0

--- GEORGESCRK.f01 (steady flow) ---

Flow Title=NFF Regression Equation
Program Version=4.00
Number of Profiles=1
Profile Names=P100yr
River Rch & RM=GEORGESCRK,Main      ,3637.3
870.6299
River Rch & RM=GEORGESCRK,Main      ,3419.5
903.6022
River Rch & RM=GEORGESCRK,Main      ,216.4
973.6084
Boundary for River Rch & Prof#=GEORGESCRK,Main      ,1
Up Type=0
Dn Type=3
Dn Slope=0.031228

--- GEORGESCRK.g01 (geometry) ---

Geom Title=USGS 10m DEM
Program Version=4.10

River Reach=GEORGESCRK      ,Main
Reach XY= 30
     1717101.944      311658.692     1717052.141      311727.026
     1717025.502      311823.157     1716939.795      311871.801
     1716900.416       311943.61     1716839.032      312024.684
     1716829.766      312071.012      1716782.28        312104.6
     1716705.838      312134.714     1716680.358      312168.301
     1716702.364      312342.032     1716690.782       312420.79
     1716600.442      312595.679     1716578.436      312664.012
     1716520.526      312983.676     1716504.311       313026.53
     1716439.452      313098.339     1716405.864      313248.905
     1716321.315      313444.641     1716278.461       313516.45
     1716222.868      313660.067     1716224.026      313801.368
     1716211.286       313851.17     1716160.325      313960.042
     1716133.686      313999.421     1715935.633      314196.315
     1715767.694      314336.458     1715504.782      314500.922
     1715454.979      314562.308     1715419.075      314650.331

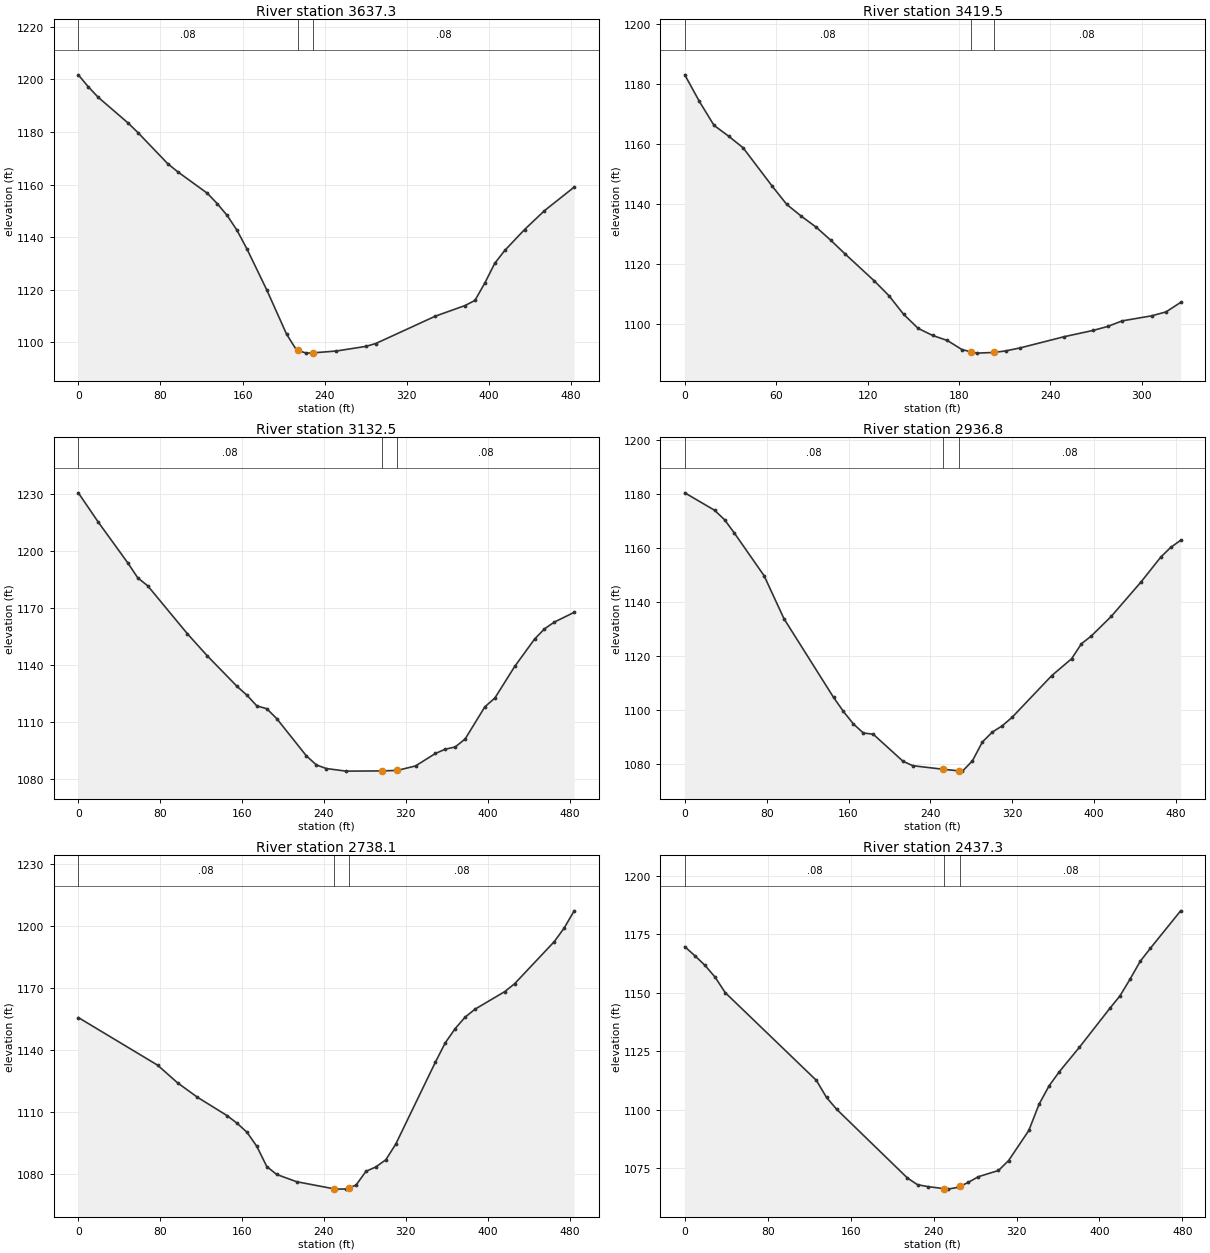
Type RM Length L Ch R = 1 ,3637.3  ,218.1,217.8,218.4
XS GIS Cut Line= 2
     1716923.985      311526.983     1717298.773      311831.503
#Sta/Elev= 30
       0 1201.66     9.7 1197.12    19.3 1193.15    48.3 1183.42      58 1179.75
    86.9 1167.98    96.6 1164.89   125.6 1156.69   135.2 1152.78   144.9 1148.28
   154.5 1142.64   164.2 1135.55   183.5 1119.99   202.8 1103.18   212.5 1097.14
   213.7 1096.99   222.1 1095.96   228.7 1096.07   251.1 1096.75   280.1 1098.53
   289.7 1099.61   347.7    1110   376.7 1114.04   386.3 1115.99     396 1122.67
   405.6  1130.1   415.3 1134.95   434.6  1142.9   453.9 1150.04   482.9 1159.01
#Mann= 3 , 0 , 0
       0     .08       0   213.7    .045       0   228.7     .08       0
Bank Sta=213.7,228.7
XS Rating Curve= 0 ,0
Exp/Cntr=0.3,0.1

Type RM Length L Ch R = 1 ,3419.5  ,281.2,286.9,290.9
XS GIS Cut Line= 2
     1716841.844      311717.939      1717088.33      311930.726
#Sta/Elev= 30
       0 1182.99     9.6  1174.1    19.2 1166.14    28.7 1162.58    38.3 1158.66
    57.5 1145.81      67 1139.77    76.6 1135.83    86.2 1132.24    95.8 1127.88
   105.4 1123.22   124.5 1114.27   134.1 1109.34   143.7 1103.16   153.2 1098.49
   162.8  1096.1   172.4 1094.44     182  1091.4   187.8 1090.68   191.6 1090.22
   202.8 1090.44   210.7 1090.96   220.3 1091.97     249 1095.68   268.2  1097.8
   277.7 1099.11   287.3 1100.98   306.5 1102.65     316 1103.96   325.6 1107.12
#Mann= 3 , 0 , 0
       0     .08       0   187.8    .045       0   202.8     .08       0
Bank Sta=187.8,202.8
XS Rating Curve= 0 ,0
Exp/Cntr=0.3,0.1

Type RM Length L Ch R = 1 ,3132.5  ,210.6,195.7,181.7
XS GIS Cut Line= 2
     1716633.265      311836.419      1716947.65      312204.976
#Sta/Elev= 30
       0 1230.51    19.4 1215.16    48.4 1193.58    58.1 1185.75    67.8 1181.57
   106.6 1156.31     126  1144.7     155 1128.68   164.7 1124.02   174.4 1118.38
   184.1 1116.88   193.8 1111.71   222.8 1092.07   232.5 1087.33   242.2 1085.41
   261.6 1084.04   296.7 1084.15   311.7 1084.43   329.4 1086.76   348.8 1093.32
   358.5 1095.58   368.2 1096.76   377.9 1100.97   397.2 1117.91   406.9 1122.49
   426.3 1139.12   445.7 1153.52   455.4  1158.9     465 1162.48   484.4  1167.6
#Mann= 3 , 0 , 0
       0     .08       0   296.7    .045       0   311.7     .08       0
Bank Sta=296.7,311.7
XS Rating Curve= 0 ,0
Exp/Cntr=0.3,0.1

Type RM Length L Ch R = 1 ,2936.8  ,201,198.7,196.5
XS GIS Cut Line= 2
     1716429.651      312105.779     1716895.848      312237.433
#Sta/Elev= 30
       0 1180.36    29.1 1173.92    38.8 1170.44    48.4 1165.51    77.5 1149.71
    96.9 1133.83   145.3 1104.78     155 1099.55   164.7 1094.96   174.4 1091.61
   184.1 1091.15   213.2 1081.15   222.8 1079.51   252.6 1078.19   267.6 1077.61
   271.3 1077.51     281 1081.31   290.7 1088.27   300.4 1091.93     310 1094.23
   319.7 1097.37   358.5 1112.81   377.9 1119.05   387.5 1124.59   397.2 1127.47
   416.6 1134.69   445.7 1147.41     465 1156.61   474.7 1160.18   484.4 1162.83
#Mann= 3 , 0 , 0
       0     .08       0   252.6    .045       0   267.6     .08       0
Bank Sta=252.6,267.6
XS Rating Curve= 0 ,0
Exp/Cntr=0.3,0.1

Type RM Length L Ch R = 1 ,2738.1  ,298.6,300.8,303
XS GIS Cut Line= 2
     1716447.969      312326.901     1716924.589      312413.532
#Sta/Elev= 30
       0 1155.85    77.5 1132.77    96.9 1124.25   116.3 1117.28   145.3 1108.37
     155 1104.71   164.7 1100.35   174.4 1093.47   184.1 1083.72   193.8 1079.86
   213.2 1076.37   249.3 1072.96   251.9 1072.77   261.6 1072.84   264.3 1073.37
   271.3 1074.72     281 1081.38   290.7 1083.54   300.4 1086.98     310 1094.47
   348.8 1134.21   358.5 1143.62   368.2 1150.51   377.9 1156.05   387.5 1159.88
   416.6  1168.4   426.3 1172.25     465 1192.62   474.7 1199.23   484.4 1207.51
#Mann= 3 , 0 , 0
       0     .08       0   249.3    .045       0   264.3     .08       0
Bank Sta=249.3,264.3
XS Rating Curve= 0 ,0
Exp/Cntr=0.3,0.1

Type RM Length L Ch R = 1 ,2437.3  ,398.1,400,401.9
XS GIS Cut Line= 2
     1716335.544      312576.259     1716795.363      312708.069
#Sta/Elev= 30
       0 1169.71     9.8 1165.82    19.5 1161.72    29.3 1156.64      39 1150.05
   126.9 1112.52   136.7 1105.22   146.4 1100.18   214.8 1070.71   224.5 1067.87
   234.3 1067.06   250.5 1066.15   253.8 1065.97   263.6 1066.74   265.5 1067.15
   273.3 1068.82   283.1 1071.27   302.6 1073.95   312.4 1078.22   331.9  1091.1
   341.7 1102.28   351.4 1110.16   361.2 1116.16   380.7  1126.7     410 1143.32
   419.8 1148.69   429.5  1155.8   439.3 1163.45     449 1168.97   478.3 1185.06
#Mann= 3 , 0 , 0
       0     .08       0   250.5    .045       0   265.5     .08       0
Bank Sta=250.5,265.5
XS Rating Curve= 0 ,0
Exp/Cntr=0.3,0.1

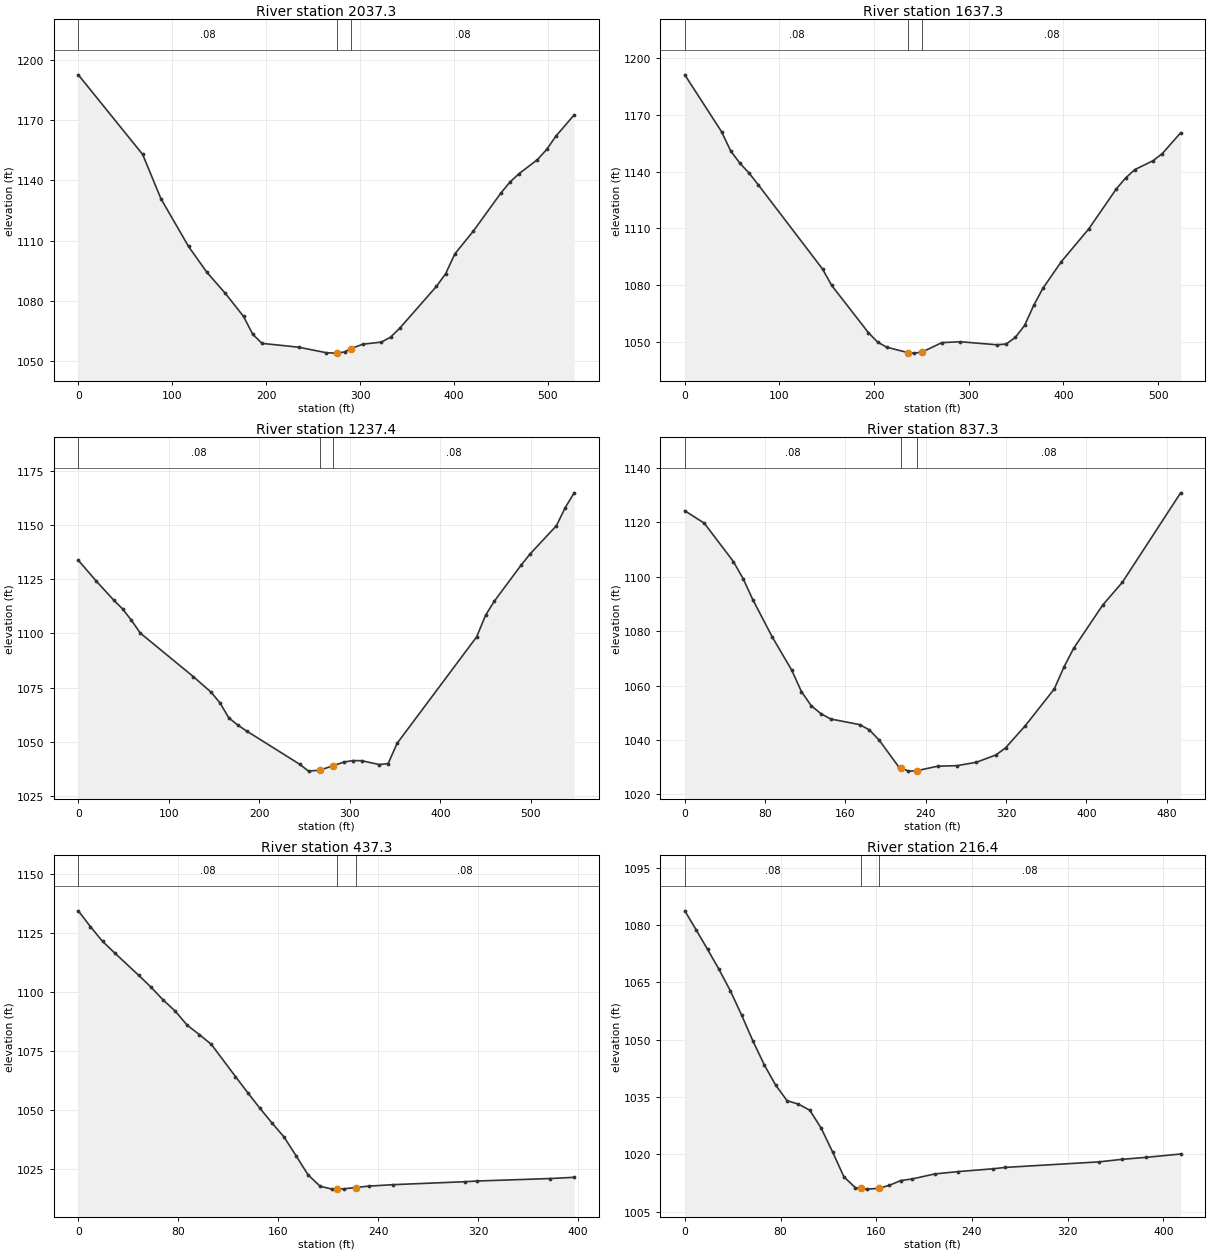
Type RM Length L Ch R = 1 ,2037.3  ,399.2,400,400.8
XS GIS Cut Line= 2
     1716233.719      312934.582     1716726.679      313124.108
#Sta/Elev= 30
       0 1192.53    68.5 1152.96      88 1130.92   117.4 1107.17   136.9 1094.36
   156.5  1083.9     176 1072.36   185.8 1063.48   195.6    1059   234.7 1057.09
   264.1 1054.34   273.8 1054.14   275.1 1054.22   283.6 1054.73   290.1 1056.37
   303.2 1058.59   322.8 1059.63   332.5 1062.08   342.3 1066.52   381.4 1087.33
   391.2 1093.61     401 1103.48   420.6 1114.75   449.9 1133.65   459.7 1139.19
   469.5 1143.42     489 1150.36   498.8 1155.42   508.6    1162   528.1 1172.61
#Mann= 3 , 0 , 0
       0     .08       0   275.1    .045       0   290.1     .08       0
Bank Sta=275.1,290.1
XS Rating Curve= 0 ,0
Exp/Cntr=0.3,0.1

Type RM Length L Ch R = 1 ,1637.3  ,406,399.9,393.7
XS GIS Cut Line= 2
     1716116.298        313298.3     1716598.598      313502.711
#Sta/Elev= 30
       0 1191.33    38.8 1161.26    48.5 1151.03    58.2 1144.56    67.9 1139.33
    77.6 1133.14   145.5 1088.54   155.2 1079.82     194 1054.83   203.7 1049.82
   213.4 1047.14   235.7 1044.27   242.5    1044   250.7 1044.58   271.6 1049.56
     291 1050.02   329.8 1048.42   339.5 1048.82   349.2 1052.34   358.9 1058.63
   368.6 1069.27   378.3 1078.33   397.7 1092.38   426.8 1109.81   455.9 1130.96
   465.6 1136.66   475.3 1141.14   494.7 1145.87   504.4 1149.62   523.8 1160.64
#Mann= 3 , 0 , 0
       0     .08       0   235.7    .045       0   250.7     .08       0
Bank Sta=235.7,250.7
XS Rating Curve= 0 ,0
Exp/Cntr=0.3,0.1

Type RM Length L Ch R = 1 ,1237.4  ,388.1,400.1,412.2
XS GIS Cut Line= 2
     1715952.067      313731.215     1716495.304      313802.233
#Sta/Elev= 30
       0 1133.74    19.6 1124.22    39.1 1115.35    48.9  1111.3    58.7 1106.01
    68.5 1100.12   127.2 1079.99   146.8 1072.81   156.5 1067.93   166.3    1061
   176.1 1057.73   185.9 1054.96   244.6 1039.61   254.4 1036.43   266.8 1036.89
   281.8 1038.95   293.5 1040.63   303.3 1041.28   313.1 1041.25   332.6 1039.45
   342.4 1039.94   352.2 1049.22   440.2 1098.42     450 1108.36   459.8 1114.92
   489.2 1131.44   498.9  1136.5   528.3 1149.69   538.1 1158.06   547.9 1164.85
#Mann= 3 , 0 , 0
       0     .08       0   266.8    .045       0   281.8     .08       0
#XS Ineff= 2 , 0
                          312.76          1040.1
Permanent Ineff=
       F       F
Bank Sta=266.8,281.8
XS Rating Curve= 0 ,0
Exp/Cntr=0.3,0.1

Type RM Length L Ch R = 1 ,837.3   ,396.7,400,403.3
XS GIS Cut Line= 2
     1715852.682      313963.994     1716242.271      314267.741
#Sta/Elev= 30
       0 1124.21    19.4 1119.65    48.4 1105.57    58.1 1099.28    67.8 1091.53
    87.2 1077.81   106.6 1065.61   116.2 1057.79   125.9 1052.64   135.6 1049.68
   145.3 1047.73   174.4 1045.64     184 1043.69   193.7 1039.94   213.1 1030.16
   215.9  1029.7   222.8 1028.57   230.9  1028.7   251.8 1030.37   271.2 1030.58
   290.6 1031.84     310 1034.51   319.6 1037.13     339 1045.15   368.1 1058.75
   377.8 1066.85   387.5 1073.73   416.5 1089.64   435.9 1097.91     494  1130.8
#Mann= 3 , 0 , 0
       0     .08       0   215.9    .045       0   230.9     .08       0
Bank Sta=215.9,230.9
XS Rating Curve= 0 ,0
Exp/Cntr=0.3,0.1

Type RM Length L Ch R = 1 ,437.3   ,216.1,220.9,225.7
XS GIS Cut Line= 2
     1715579.485      314206.913     1715852.864      314494.631
#Sta/Elev= 29
       0 1134.24     9.7 1127.55    19.4 1121.33      29  1116.5    48.4 1106.95
    58.1 1102.04    67.8 1096.62    77.4 1091.97    87.1 1085.95    96.8 1081.98
   106.5 1077.81   125.8 1064.22   135.5 1057.48   145.2 1050.92   154.9  1044.7
   164.6 1038.73   174.2 1030.85   183.9  1022.7   193.6 1017.84   203.3 1016.66
     207 1016.72     213 1016.82     222 1017.34   232.3 1017.92   251.7 1018.54
   309.8  1019.8   319.4 1020.09   377.5 1021.13   396.9 1021.65
#Mann= 3 , 0 , 0
       0     .08       0     207    .045       0     222     .08       0
Bank Sta=207,222
XS Rating Curve= 0 ,0
Exp/Cntr=0.3,0.1

Type RM Length L Ch R = 1 ,216.4   ,220.1,201.8,182.2
XS GIS Cut Line= 3
     1715456.312      314342.851     1715565.536      314521.004
     1715767.019      314561.301
#Sta/Elev= 30
       0 1083.72     9.5 1078.74      19 1073.65    28.5 1068.45      38 1062.84
    47.5 1056.42      57 1049.62    66.5 1043.39      76 1038.08    85.5 1034.04
      95 1033.13   104.5 1031.55     114 1026.84   123.5 1020.65     133 1014.11
   142.5  1011.3     147 1011.11     152  1010.9     162  1011.1     171  1011.9
   180.5 1013.15     190 1013.56     209 1014.88   228.5 1015.49   257.9 1016.23
   267.7 1016.58     346 1018.03   365.5  1018.7   385.1  1019.2   414.4 1020.09
#Mann= 3 , 0 , 0
       0     .08       0     147    .045       0     162     .08       0
Bank Sta=147,162
XS Rating Curve= 0 ,0
Exp/Cntr=0.3,0.1

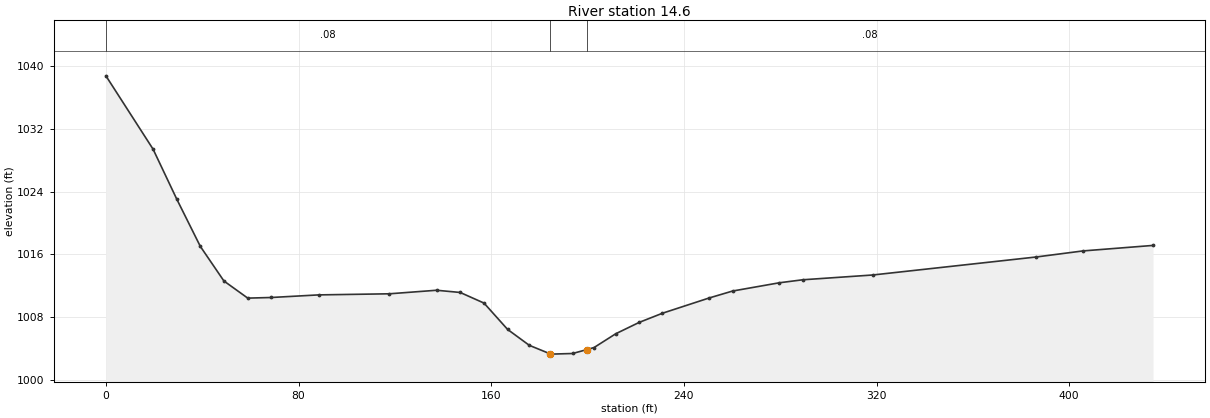
Type RM Length L Ch R = 1 ,14.6    ,10.5,14.6,20
XS GIS Cut Line= 4
     1715318.852      314485.787     1715399.959      314631.497
     1715443.923      314640.981     1715665.217      314613.262
#Sta/Elev= 30
       0 1038.71    19.6 1029.38    29.4 1023.05    39.2 1017.03      49 1012.63
    58.9 1010.45    68.7 1010.53    88.3 1010.86   117.7    1011   137.3 1011.45
   147.1 1011.17     157 1009.82   166.8 1006.47   175.8 1004.45   184.6 1003.35
   184.8 1003.33   193.8 1003.41   199.6  1003.9   202.7 1004.17   211.7 1005.92
   221.4 1007.36   231.1 1008.53   250.5 1010.47   260.2 1011.35   279.6  1012.4
   289.3 1012.78   318.4 1013.39   386.3 1015.68   405.7 1016.45   434.8 1017.15
#Mann= 3 , 0 , 0
       0     .08       0   184.6    .045       0   199.6     .08       0
Bank Sta=184.6,199.6
XS Rating Curve= 0 ,0
Exp/Cntr=0.3,0.1

Chan Stop Cuts=-1
Use User Specified Reach Order=0
Composite Channel Slope=5